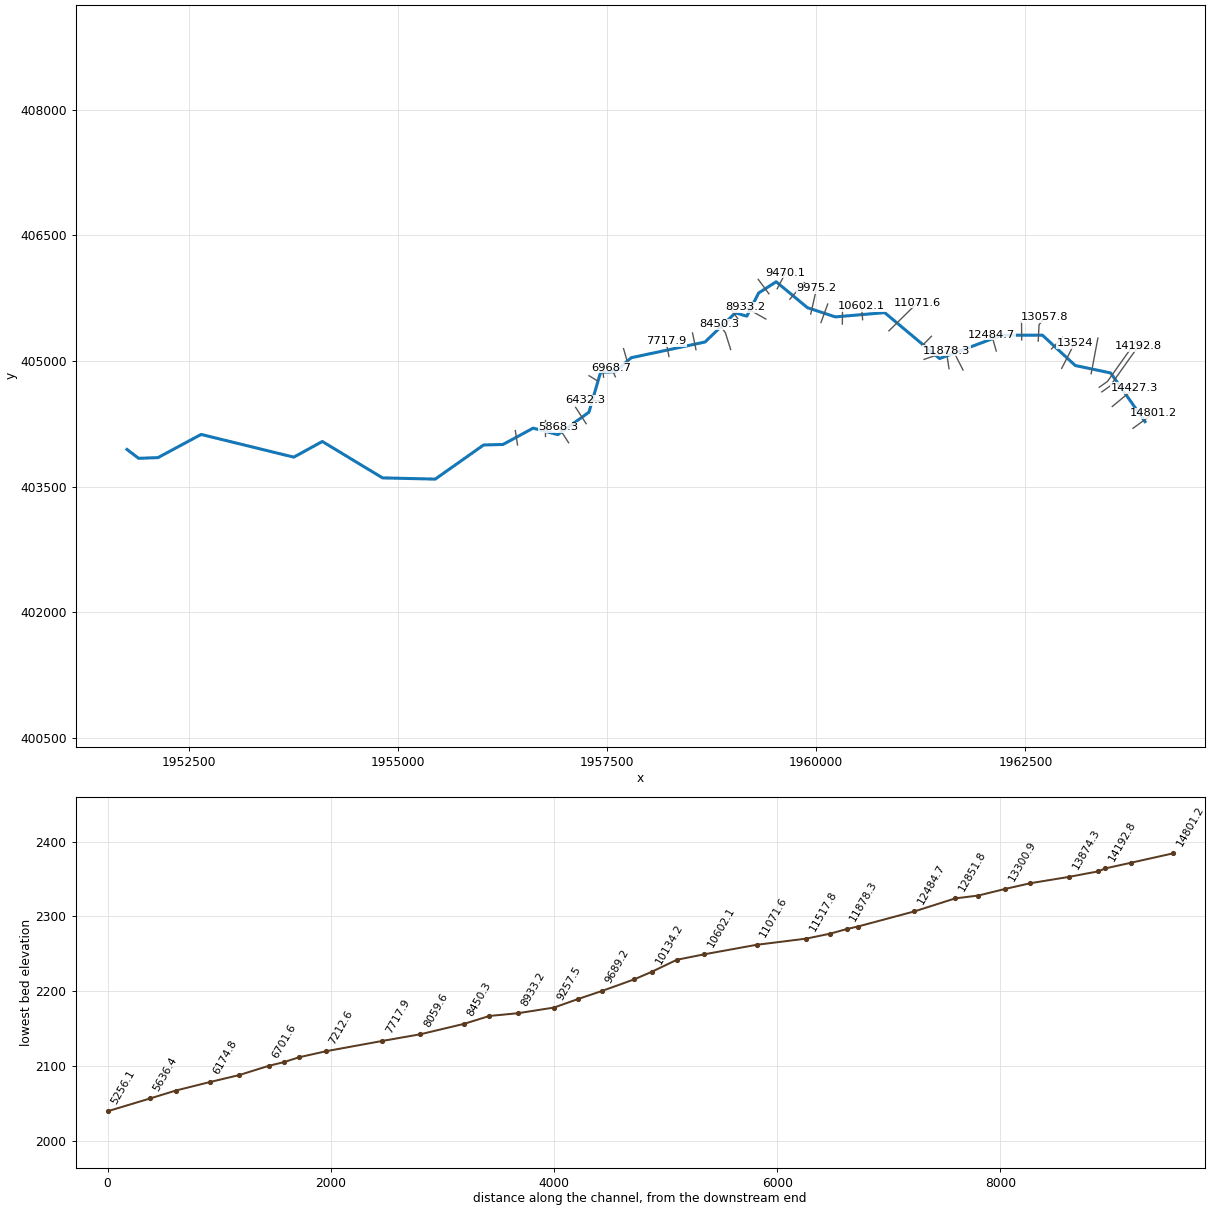
--- BEAVERCRK.prj (project) ---

Proj Title=BEAVERCRK
Current Plan=p01
Geom File=g01
Flow File=f01
Plan File=p01
DSS Export Rating Curves=0
DSS Export Rating Curve Sorted=0
DSS Export Volume Flow Curves=0
DXF OffsetX=0
DXF OffsetY=0
DXF ScaleX=0
DXF ScaleY=0

--- BEAVERCRK.p01 (plan) ---

Plan Title=Floodplain
Program Version=4.00
Geom File=g01
Flow File=f01
K Sum by GR=0
Std Step Tol=0.01
Critical Tol=0.01
Num of Std Step Trials=20
Max Error Tol=0.3
Flow Tol Ratio=0.001
Split Flow NTrial=30
Split Flow Tol=0.02
Split Flow Ratio=0.02
Log Output Level=0
Friction Slope Method=1
Unsteady Friction Slope Method=2
Unsteady Bridges Friction Slope Method=1
Global Log Level=0
CheckData=False
Run HTab=0
Run UNet=0
Run PostProcess=0
UNET Theta=0
UNET Theta Warmup=0
UNET ZTol=0
UNET ZSATol=0
UNET MxIter=0
UNET MaxInSteps=0
UNET DtIC=0
UNET DtMin=0
UNET MaxCRTS=0
UNET WFStab=0
UNET SFStab=0
UNET WFX=0
UNET SFX=0
UNET DSS MLevel=0
UNET DZMax Abort=0
UNET Convert EG Bridges=0
UNET Use Existing IB Tables=0
UNET Froude Limit=0
UNET Froude Power=0
Write IC File=0
Echo Input=False
Echo Output=False
Write Detailed=0

--- BEAVERCRK.f01 (steady flow) ---

Flow Title=NFF Regression Equation
Program Version=4.10
Number of Profiles= 1
Profile Names=P100yr
River Rch & RM=BEAVERCRK,Main            ,14801.2
518.2988
River Rch & RM=BEAVERCRK,Main            ,13874.3
558.4601
River Rch & RM=BEAVERCRK,Main            ,13524
593.8689
River Rch & RM=BEAVERCRK,Main            ,11517.8
642.6786
River Rch & RM=BEAVERCRK,Main            ,8450.3
712.2556
River Rch & RM=BEAVERCRK,Main            ,5636.4
772.4948
River Rch & RM=BEAVERCRK,Main            ,5256.1
775.5241
River Rch & RM=BEAVERCRK,Main            ,533.3
860.5189
Boundary for River Rch & Prof#=BEAVERCRK,Main            , 1
Up Type= 0
Dn Type= 1
Dn Known WS=1878.47
DSS Import GetInterval= 0
DSS Import GetPeak= 0
DSS Import FillOption= 0

--- BEAVERCRK.g01 (geometry) ---

Geom Title=USGS 10m DEM
Program Version=4.10

River Reach=BEAVERCRK       ,Main
Reach XY= 30
     1963929.183       404276.49      1963518.55      404857.799
     1963094.846      404946.896      1962702.89      405309.292
     1962215.558      405308.031     1961473.498      405029.821
      1960817.71      405578.226      1960228.58      405527.401
     1959894.797      405637.032     1959520.751      405946.927
     1959311.105       405812.81     1959169.546      405535.919
     1959033.263      405575.668     1958669.955      405227.322
     1957788.259       405039.62     1957595.191      404872.106
     1957421.998      404866.427     1957282.824      404388.871
     1956910.936      404121.413     1956616.366      404198.948
     1956256.319      404003.883     1956024.015      403997.564
     1955445.832      403590.078     1954815.582      403604.672
     1954096.173      404039.298     1953755.414      403852.256
     1952647.435      404123.573        1952132.      403846.583
     1951900.352      403838.293     1951761.463      403944.196

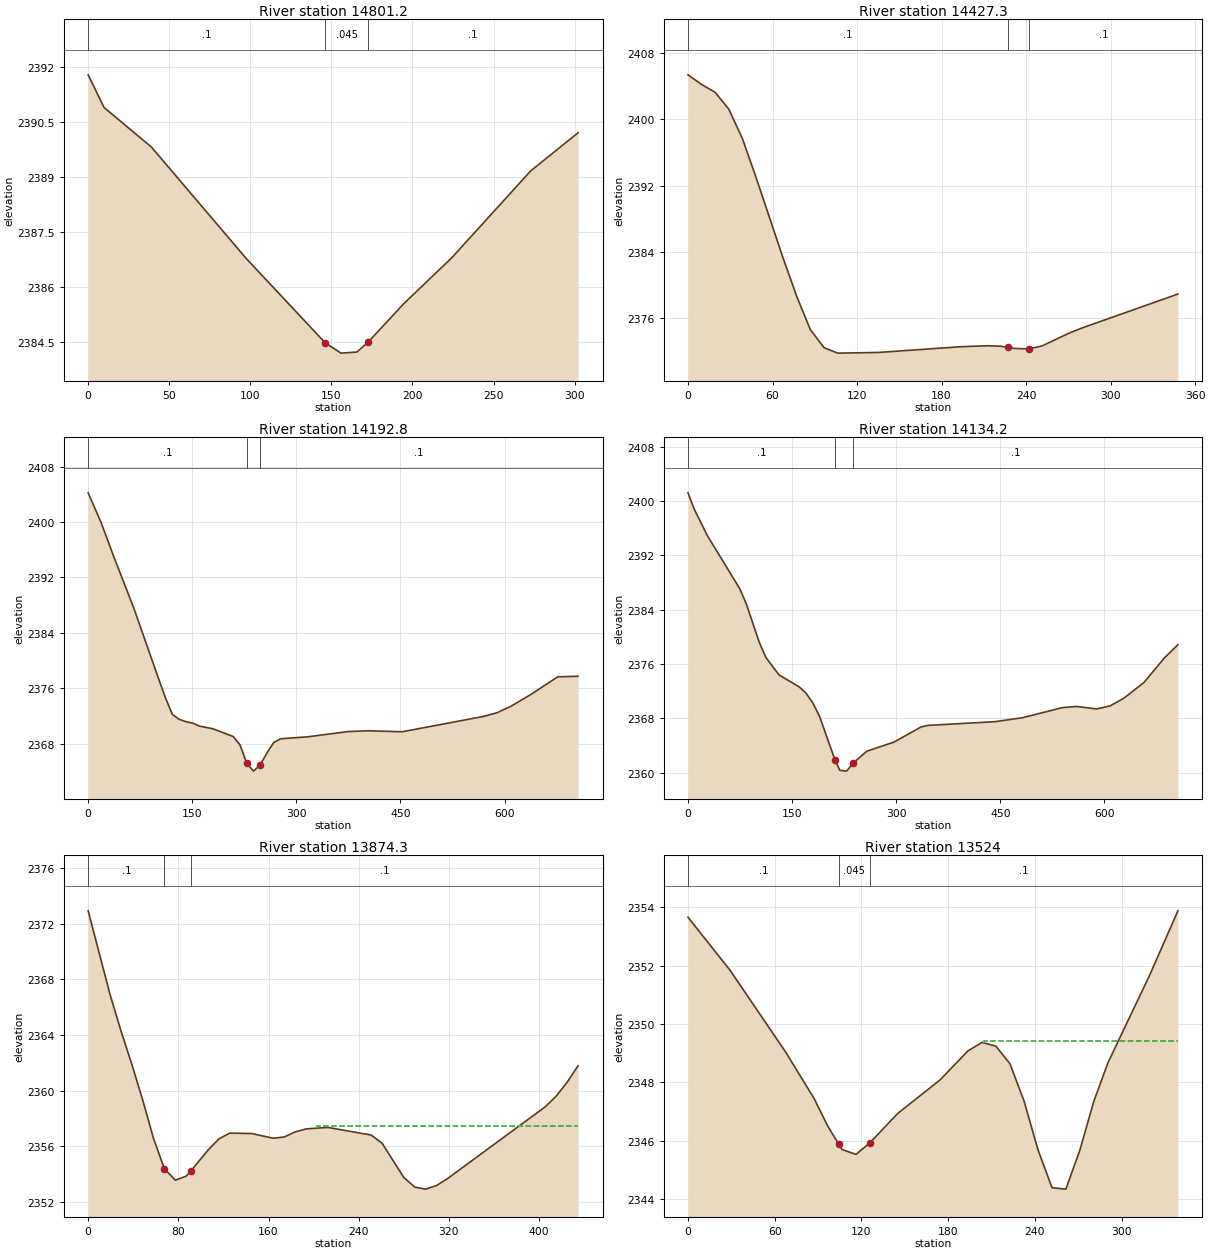
Type RM Length L Ch R = 1 ,14801.2 ,372.1,373.9,375
XS GIS Cut Line= 2
     1963785.422      404196.927     1964030.213      404374.011
#Sta/Elev= 12
       0 2391.79     9.8  2390.9      39 2389.82    97.5 2386.78   146.2 2384.48
   155.9  2384.2   165.7 2384.23   172.4 2384.49   194.9 2385.56   224.2  2386.8
   272.9 2389.17   302.1 2390.21
#Mann= 3 , 0 , 0
       0      .1       0   146.2    .045       0   172.4      .1       0
Bank Sta=146.2,172.4
XS Rating Curve= 0 ,0
Exp/Cntr=0.3,0.1

Type RM Length L Ch R = 1 ,14427.3 ,228.4,234.5,240.5
XS GIS Cut Line= 2
     1963538.026      404457.344     1963806.255      404678.698
#Sta/Elev= 22
       0 2405.39     9.7 2404.22    19.3 2403.27      29 2401.23    38.6  2397.7
    48.3 2392.99    67.6  2383.2    77.3 2378.56    86.9 2374.58    96.6 2372.41
   106.3 2371.75   135.2 2371.83   193.2 2372.52   212.5 2372.64   222.2 2372.58
   227.1 2372.45   231.8 2372.32   242.1 2372.26   251.2 2372.61   270.5 2374.16
   280.2 2374.82   347.8 2378.89
#Mann= 3 , 0 , 0
       0      .1       0   227.1    .045       0   242.1      .1       0
Bank Sta=227.1,242.1
XS Rating Curve= 0 ,0
Exp/Cntr=0.3,0.1

Type RM Length L Ch R = 1 ,14192.8 ,58.7,58.6,58.6
XS GIS Cut Line= 3
     1963413.026      404631.823     1963511.984      404702.136
     1963850.526      405178.698
#Sta/Elev= 30
       0 2404.21    18.7 2399.91    37.4 2394.88    65.4 2387.68   102.7 2377.04
   112.1 2374.45   121.4 2372.22   131.1 2371.54   140.9 2371.18   150.6 2370.98
   160.4 2370.55   179.8 2370.16   209.1 2369.04   218.8 2367.85   228.6 2365.16
   238.3 2364.05     248 2364.96   257.8  2366.7   267.5 2368.18   277.3 2368.72
   316.2    2369   374.7 2369.76   403.9 2369.87   452.6 2369.73   569.6 2371.94
     589 2372.47   608.5 2373.37   637.8  2375.1   676.7 2377.66     706 2377.74
#Mann= 3 , 0 , 0
       0      .1       0   228.6    .045       0     248      .1       0
Bank Sta=228.6,248
XS Rating Curve= 0 ,0
Exp/Cntr=0.3,0.1

Type RM Length L Ch R = 1 ,14134.2 ,250.1,259.8,269.6
XS GIS Cut Line= 3
     1963381.776      404686.511     1963480.734      404756.823
     1963819.276      405233.386
#Sta/Elev= 30
       0 2401.21     9.3 2398.73      28 2394.89    74.7 2387.08      84 2384.88
   102.7 2379.22   112.1    2377   131.1 2374.42   160.4 2372.64   170.1 2371.72
   179.8  2370.3   189.6 2368.31   211.8  2361.9   218.8 2360.36   228.6 2360.25
   238.3 2361.46   257.8 2363.19   296.8 2364.52   335.7 2366.74   345.5 2366.98
   442.9 2367.53   481.9 2368.11   540.3 2369.61   559.8 2369.77     589  2369.4
   608.5 2369.86     628 2370.97   657.2 2373.31   686.5 2376.91     706 2378.85
#Mann= 3 , 0 , 0
       0      .1       0   211.8    .045       0   238.3      .1       0
Bank Sta=211.8,238.3
XS Rating Curve= 0 ,0
Exp/Cntr=0.3,0.1

Type RM Length L Ch R = 1 ,13874.3 ,357.1,350.4,343.6
XS GIS Cut Line= 2
     1963285.422      404847.969     1963366.151      405275.052
#Sta/Elev= 30
       0 2372.91    19.3 2366.94      29 2364.32    38.6 2361.93    48.3 2359.36
      58 2356.57    67.6 2354.41    77.3 2353.58    86.9 2353.87    91.3 2354.26
   106.2 2355.73   115.9 2356.54   125.6 2356.96   144.9 2356.93   164.2 2356.59
   173.9 2356.68   183.5 2357.04   193.2 2357.26   212.5 2357.37   251.1 2356.82
   260.8 2356.23   280.1 2353.77   289.8 2353.08   299.4 2352.94   309.1  2353.2
   318.7 2353.69   405.7 2358.86   415.3 2359.62     425 2360.62   434.6 2361.79
#Mann= 3 , 0 , 0
       0      .1       0    67.6    .045       0    91.3      .1       0
#XS Ineff= 2 , 0
                          202.82         2357.48
Permanent Ineff=
       F       F
Bank Sta=67.6,91.3
XS Rating Curve= 0 ,0
Exp/Cntr=0.3,0.1

Type RM Length L Ch R = 1 ,13524   ,230.1,223.1,216
XS GIS Cut Line= 2
     1962933.859      404913.073     1963087.505      405215.157
#Sta/Elev= 24
       0 2353.66      29 2351.85    67.8 2349.02    87.2 2347.45    96.8 2346.49
   104.3 2345.88   106.5  2345.7   116.2 2345.53   125.9 2345.93   145.2 2346.94
   174.3 2348.08   193.7 2349.08   203.4 2349.37     213 2349.24   222.7 2348.64
   232.4 2347.37   242.1 2345.69   251.8 2344.39   261.4 2344.34   271.1 2345.68
   280.8 2347.36   290.5 2348.67   319.6  2351.7   338.9 2353.88
#Mann= 3 , 0 , 0
       0      .1       0   104.3    .045       0   125.9      .1       0
#XS Ineff= 2 , 0
                          204.58         2349.41
Permanent Ineff=
       F       F
Bank Sta=104.3,125.9
XS Rating Curve= 0 ,0
Exp/Cntr=0.3,0.1

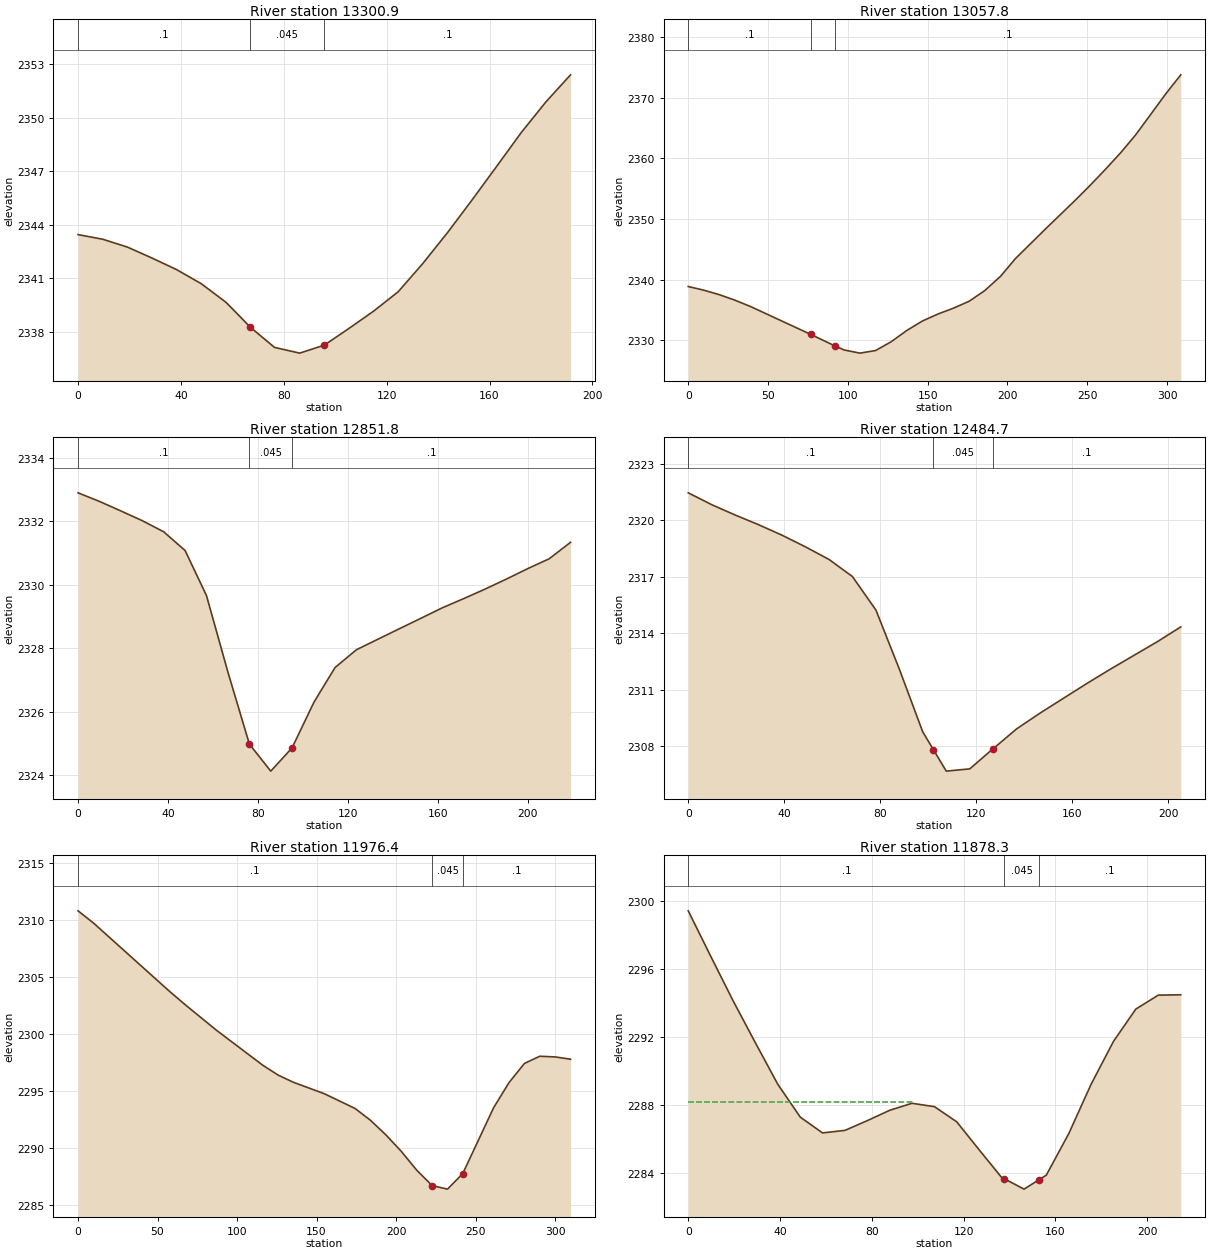
Type RM Length L Ch R = 1 ,13300.9 ,226.9,243.1,259.3
XS GIS Cut Line= 2
     1962811.463      405144.844     1962944.276      405282.865
#Sta/Elev= 22
       0 2343.45     9.6 2343.19    19.2 2342.75    28.7 2342.14    38.3 2341.49
    47.9  2340.7    57.5 2339.66    61.4 2339.09      67 2338.26    76.4 2337.13
    86.2 2336.81    95.8 2337.26   105.4  2338.2   114.9 2339.16   124.5 2340.25
   134.1 2341.84   143.7 2343.57   153.2 2345.39   162.8 2347.28   172.4 2349.18
     182  2350.9   191.5  2352.4
#Mann= 3 , 0 , 0
       0      .1       0      67    .045       0    95.8      .1       0
Bank Sta=67,95.8
XS Rating Curve= 0 ,0
Exp/Cntr=0.3,0.1

Type RM Length L Ch R = 1 ,13057.8 ,204.6,206,207.5
XS GIS Cut Line= 3
     1962652.609      405238.594     1962663.026      405433.907
     1962733.338      405522.448
#Sta/Elev= 27
       0 2338.88     9.8 2338.27    19.6 2337.52    29.3 2336.62    39.1 2335.57
    76.8 2330.98    91.8  2329.1    97.8 2328.41   107.6  2327.9   117.4 2328.33
   127.1 2329.77   136.9 2331.63   146.7 2333.19   156.5 2334.35   166.2 2335.31
     176 2336.45   185.8 2338.21   195.6 2340.54     205 2343.48   223.9 2348.38
   242.7 2353.15   252.1 2355.63   261.5 2358.22     271 2360.94   280.4 2363.89
   299.2 2370.63   308.6 2373.76
#Mann= 3 , 0 , 0
       0      .1       0    76.8    .045       0    91.8      .1       0
Bank Sta=76.8,91.8
XS Rating Curve= 0 ,0
Exp/Cntr=0.3,0.1

Type RM Length L Ch R = 1 ,12851.8 ,360.6,367,372.8
XS GIS Cut Line= 2
     1962455.534      405252.964     1962453.228      405471.987
#Sta/Elev= 26
       0  2332.9     9.5 2332.63      19 2332.33    28.6 2332.02    38.1 2331.67
    47.6 2331.08    57.1 2329.66    66.7 2327.23    76.2 2324.97    85.7 2324.12
    91.9  2324.6    95.2 2324.86   104.8 2326.28   106.9 2326.53   114.3 2327.39
   123.8 2327.95   133.3 2328.28   142.8 2328.61   152.4 2328.94   161.9 2329.27
   171.4 2329.56   180.9 2329.86   190.5 2330.18     200 2330.51   209.5 2330.82
     219 2331.34
#Mann= 3 , 0 , 0
       0      .1       0    76.2    .045       0    95.2      .1       0
Bank Sta=76.2,95.2
XS Rating Curve= 0 ,0
Exp/Cntr=0.3,0.1

Type RM Length L Ch R = 1 ,12484.7 ,503.8,508.3,513.4
XS GIS Cut Line= 2
     1962151.207      405119.244     1962095.317      405316.719
#Sta/Elev= 25
       0 2321.45     9.8 2320.82    19.6 2320.27    29.3 2319.76    39.1  2319.2
    48.9 2318.58    58.6 2317.92    68.4 2317.01    78.2 2315.23      88 2312.08
    97.7 2308.77  102.112307.834   107.5 2306.69     114 2306.77   117.3 2306.81
     127 2307.88     129 2308.09   136.8 2308.93   146.6 2309.77   156.4 2310.56
   166.1 2311.34   175.9  2312.1   185.7 2312.83   195.5 2313.56   205.2 2314.34
#Mann= 3 , 0 , 0
       0      .1       0  102.11    .045       0     127      .1       0
Bank Sta=102.11,127
XS Rating Curve= 0 ,0
Exp/Cntr=0.3,0.1

Type RM Length L Ch R = 1 ,11976.4 ,105.4,98.1,90.9
XS GIS Cut Line= 2
     1961754.172       404892.24     1961613.547      405168.282
#Sta/Elev= 23
       0 2310.84     9.7 2309.77    58.1  2303.7    67.8 2302.55    87.1 2300.35
   116.2 2297.28   125.9 2296.41   135.5 2295.78   154.9 2294.78   174.3 2293.48
   183.9 2292.45   193.6 2291.17   203.3 2289.72     213 2288.07   222.7 2286.71
   232.4  2286.4     242 2287.77   261.4 2293.55   271.1 2295.76   280.8 2297.44
   290.4 2298.07   300.1 2298.01   309.8 2297.81
#Mann= 3 , 0 , 0
       0      .1       0   222.7    .045       0     242      .1       0
Bank Sta=222.7,242
XS Rating Curve= 0 ,0
Exp/Cntr=0.3,0.1

Type RM Length L Ch R = 1 ,11878.3 ,180.5,147.5,113.7
XS GIS Cut Line= 2
     1961586.359      404909.443     1961554.082       405121.55
#Sta/Elev= 25
       0 2299.42     9.8 2296.75    19.5 2294.15    29.3 2291.66      39 2289.24
    48.8 2287.31    58.5 2286.38    68.3 2286.53      78  2287.1    87.8 2287.71
    97.5 2288.12   107.3 2287.92     117 2287.03   126.8 2285.38   136.5 2283.77
   137.7 2283.69   146.3 2283.08   152.7 2283.62     156  2283.9   165.8 2286.34
   175.5 2289.23   185.3 2291.76     195 2293.65   204.8 2294.47   214.6 2294.49
#Mann= 3 , 0 , 0
       0      .1       0   137.7    .045       0   152.7      .1       0
#XS Ineff= 2 , 0
           97.89 2288.21
Permanent Ineff=
       F       F
Bank Sta=137.7,152.7
XS Rating Curve= 0 ,0
Exp/Cntr=0.3,0.1

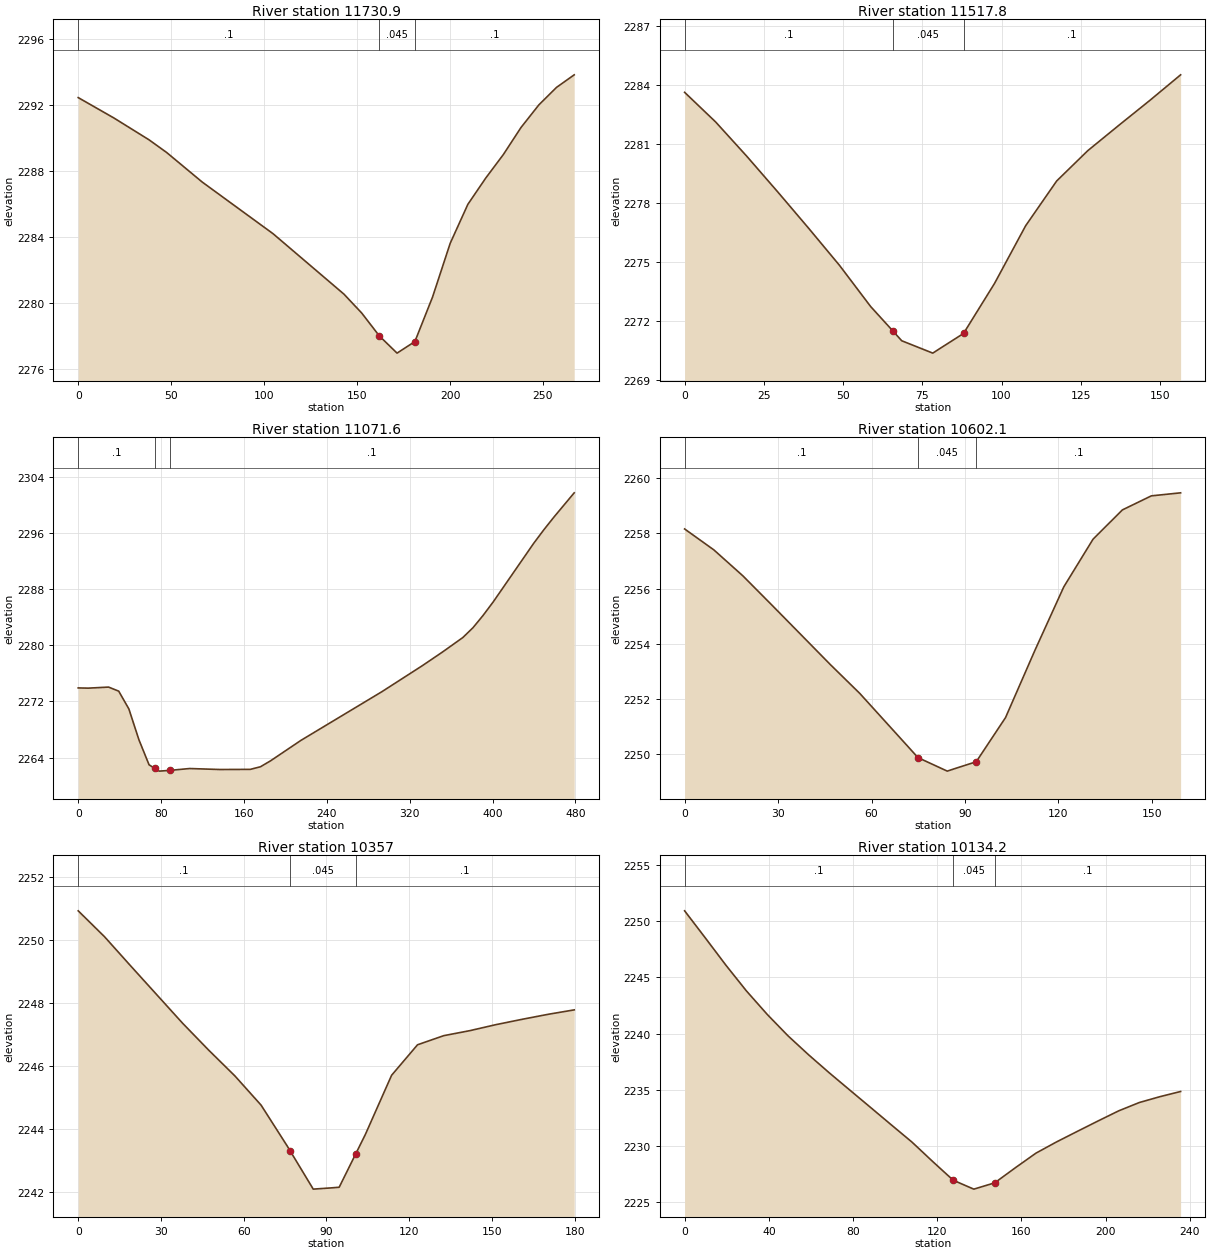
Type RM Length L Ch R = 1 ,11730.9 ,202.2,213.1,223.9
XS GIS Cut Line= 2
     1961288.026      405019.844      1961540.63      405105.782
#Sta/Elev= 20
       0 2292.47    19.1 2291.24    38.1 2289.91    47.6 2289.14    66.7 2287.35
   104.8 2284.22   142.9 2280.56   152.5 2279.41     162 2278.02   171.5 2276.98
   181.1 2277.68   190.6 2280.38   200.1 2283.64   209.6    2286   219.2 2287.59
   228.7 2289.02   238.2 2290.66   247.8 2292.03   257.3 2293.09   266.8 2293.85
#Mann= 3 , 0 , 0
       0      .1       0     162    .045       0   181.1      .1       0
Bank Sta=162,181.1
XS Rating Curve= 0 ,0
Exp/Cntr=0.3,0.1

Type RM Length L Ch R = 1 ,11517.8 ,446.4,446.2,445.9
XS GIS Cut Line= 2
     1961267.192      405183.907     1961376.567      405295.886
#Sta/Elev= 19
       0 2283.65     9.8 2282.14    19.6  2280.4    29.4 2278.58    39.1 2276.74
    48.9 2274.84    58.7 2272.75    65.7 2271.51    68.5 2271.01    78.3 2270.38
    80.7 2270.63      88 2271.38    97.8 2273.93   107.6 2276.86   117.4 2279.14
   127.2 2280.68     137 2281.97   146.8 2283.24   156.5 2284.54
#Mann= 3 , 0 , 0
       0      .1       0    65.7    .045       0      88      .1       0
Bank Sta=65.7,88
XS Rating Curve= 0 ,0
Exp/Cntr=0.3,0.1

Type RM Length L Ch R = 1 ,11071.6 ,447.8,469.5,490
XS GIS Cut Line= 2
     1960868.755       405360.99     1961209.901      405696.927
#Sta/Elev= 27
       0 2273.93     9.8  2273.9    29.3 2274.05    39.1 2273.47    48.9 2270.94
    58.6 2266.55    68.4 2262.98    73.8 2262.48    78.2 2262.08    88.8 2262.19
   107.5 2262.45   136.8 2262.31   166.1 2262.33   175.9  2262.7   185.6 2263.54
     215 2266.46   293.1 2273.39   332.2  2277.1   351.8 2279.06   371.3 2281.11
   381.1 2282.51   390.8 2284.25   400.6 2286.18   439.7 2294.53   449.5 2296.46
   459.2 2298.26   478.8 2301.72
#Mann= 3 , 0 , 0
       0      .1       0    73.8    .045       0    88.8      .1       0
Bank Sta=73.8,88.8
XS Rating Curve= 0 ,0
Exp/Cntr=0.3,0.1

Type RM Length L Ch R = 1 ,10602.1 ,246.9,245,243.2
XS GIS Cut Line= 2
     1960553.651      405493.802     1960543.234      405652.657
#Sta/Elev= 20
       0 2258.16     9.4  2257.4    18.7 2256.46    28.1 2255.39    37.5 2254.31
    46.8 2253.24    56.2  2252.2    65.6 2251.03    71.7 2250.27    74.9 2249.87
    84.3 2249.38    86.7 2249.47    93.6 2249.72     103 2251.32   112.4 2253.75
   121.7 2256.06   131.1 2257.79   140.5 2258.85   149.8 2259.36   159.2 2259.47
#Mann= 3 , 0 , 0
       0      .1       0    74.9    .045       0    93.6      .1       0
Bank Sta=74.9,93.6
XS Rating Curve= 0 ,0
Exp/Cntr=0.3,0.1

Type RM Length L Ch R = 1 ,10357   ,230.6,222.9,215.2
XS GIS Cut Line= 2
     1960311.415      405442.015      1960313.72      405621.844
#Sta/Elev= 23
       0 2250.93     9.5 2250.11    18.9 2249.19    28.4 2248.27    37.9 2247.35
    47.3  2246.5    56.8 2245.68    66.3 2244.75    75.7 2243.46    76.8  2243.3
    85.2 2242.08    91.8 2242.12    94.6 2242.14  100.562243.194   104.1 2243.82
   113.6  2245.7     123 2246.67   132.5 2246.96     142 2247.12   151.4 2247.31
   160.9 2247.48   170.4 2247.64   179.8 2247.78
#Mann= 3 , 0 , 0
       0      .1       0    76.8    .045       0  100.56      .1       0
Bank Sta=76.8,100.56
XS Rating Curve= 0 ,0
Exp/Cntr=0.3,0.1

Type RM Length L Ch R = 1 ,10134.2 ,156.1,159,161.8
XS GIS Cut Line= 2
     1960056.255      405459.948     1960136.984      405681.302
#Sta/Elev= 27
       0 2250.92     9.8 2248.52    19.6 2246.09    29.4 2243.79    39.3  2241.7
    49.1 2239.81    58.9 2238.12    68.7 2236.52    78.5 2234.98    88.4 2233.43
    98.2 2231.89     108 2230.36   117.8 2228.64   121.6 2227.99   127.6 2226.97
   136.6 2226.24   137.4 2226.18   147.3 2226.74   157.1 2228.08   166.9 2229.38
   176.7 2230.38   186.5 2231.31   196.4 2232.24   206.2 2233.14     216 2233.88
   225.8  2234.4   235.6 2234.86
#Mann= 3 , 0 , 0
       0      .1       0   127.6    .045       0   147.3      .1       0
Bank Sta=127.6,147.3
XS Rating Curve= 0 ,0
Exp/Cntr=0.3,0.1

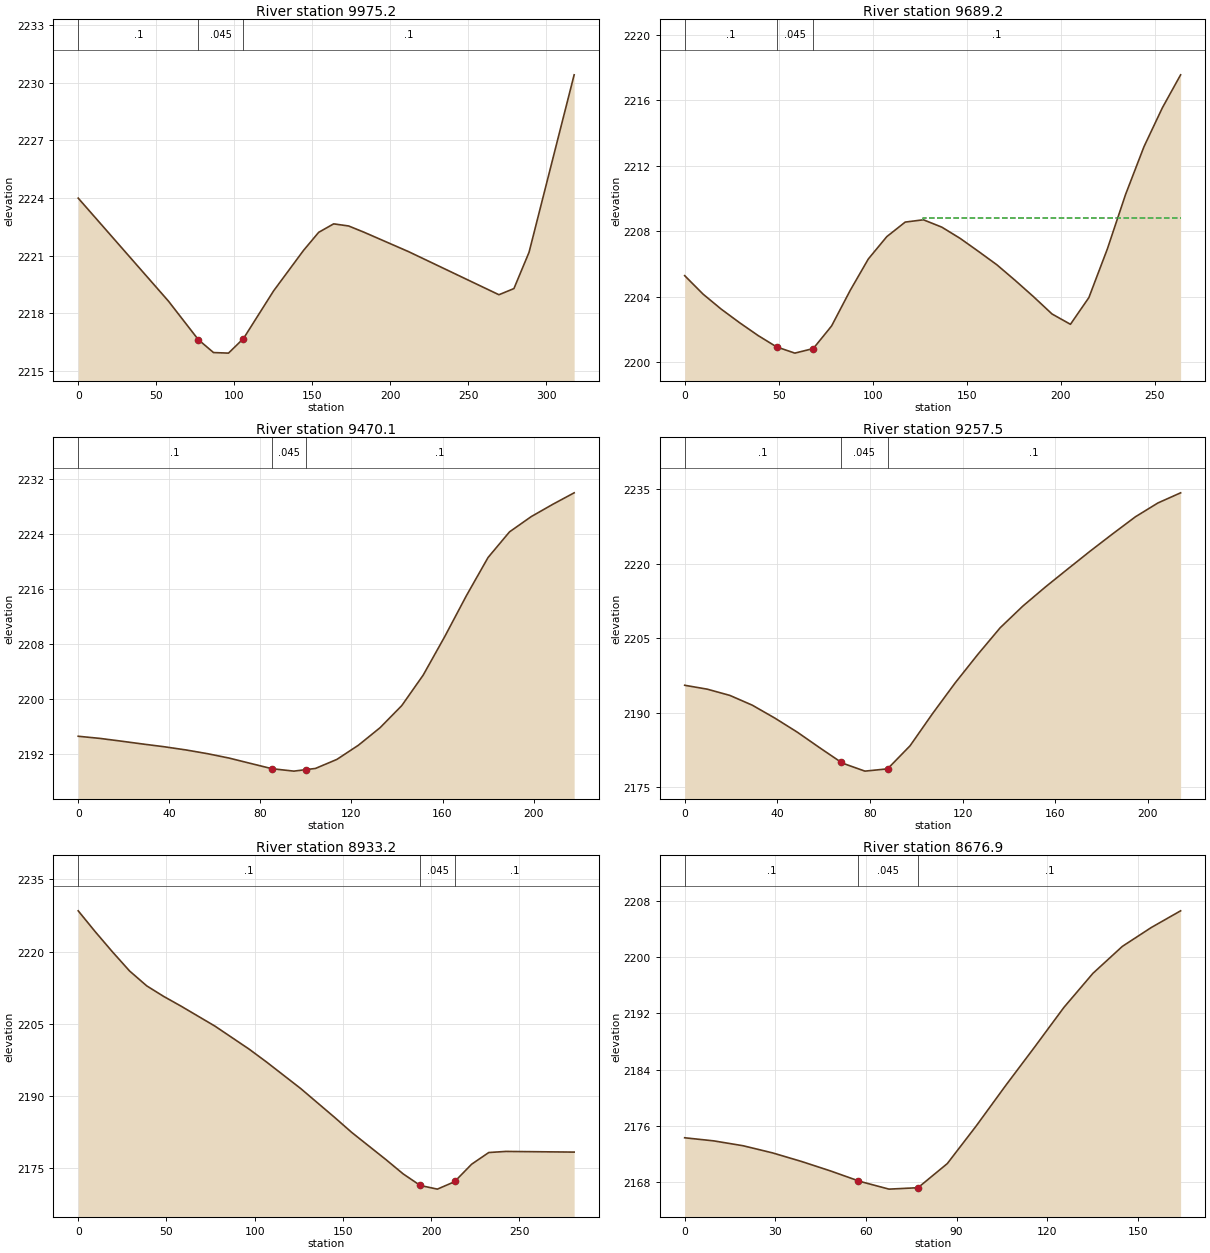
Type RM Length L Ch R = 1 ,9975.2  ,297.4,286,274.6
XS GIS Cut Line= 2
     1959933.859      405561.511     1960004.172      405871.407
#Sta/Elev= 17
       0 2223.99    57.8 2218.63      77 2216.62    86.7 2215.95    96.3 2215.92
   105.9 2216.68   125.2 2219.16   144.4 2221.27   154.1 2222.21   163.7 2222.65
   173.3 2222.54     183 2222.22   211.8  2221.2   269.6 2218.96   279.2 2219.28
   288.9 2221.17   317.8 2230.41
#Mann= 3 , 0 , 0
       0      .1       0      77    .045       0   105.9      .1       0
Bank Sta=77,105.9
XS Rating Curve= 0 ,0
Exp/Cntr=0.3,0.1

Type RM Length L Ch R = 1 ,9689.2  ,213.7,219.1,224.4
XS GIS Cut Line= 2
     1959683.859      405738.594     1959858.338      405936.511
#Sta/Elev= 30
       0  2205.3     9.8 2204.17    19.5 2203.25    29.3 2202.42    39.1 2201.64
    48.9 2200.95    58.6 2200.57    61.4 2200.65    68.4 2200.85    76.4 2201.98
    78.2 2202.24      88 2204.39    97.7 2206.32   107.5 2207.68   117.3 2208.57
     127 2208.71   136.8 2208.26   146.6 2207.57   156.4 2206.77   166.1 2205.96
   175.9    2205   185.7    2204   195.4 2202.96   205.2 2202.33     215 2203.96
   224.8 2206.92   234.5 2210.25   244.3 2213.17   254.1 2215.55   263.8 2217.56
#Mann= 3 , 0 , 0
       0      .1       0    48.9    .045       0    68.4      .1       0
#XS Ineff= 2 , 0
                          126.76         2208.79
Permanent Ineff=
       F       F
Bank Sta=48.9,68.4
XS Rating Curve= 0 ,0
Exp/Cntr=0.3,0.1

Type RM Length L Ch R = 1 ,9470.1  ,186.2,212.6,238.6
XS GIS Cut Line= 2
     1959532.817      405863.594      1959634.38      406056.302
#Sta/Elev= 25
       0 2194.63     9.5 2194.32    18.9 2193.92    28.4  2193.5    37.9  2193.1
    47.4 2192.64    56.8  2192.1    66.3 2191.46    75.8 2190.68    85.1 2189.92
    94.7 2189.57   100.1 2189.79   104.2 2189.96   113.6 2191.27   123.1 2193.34
   132.6 2195.88   142.1 2199.08   151.5  2203.5     161 2209.11   170.5 2215.04
     180 2220.57   189.4 2224.28   198.9 2226.49   208.4 2228.28   217.8 2229.95
#Mann= 3 , 0 , 0
       0      .1       0    85.1    .045       0   100.1      .1       0
Bank Sta=85.1,100.1
XS Rating Curve= 0 ,0
Exp/Cntr=0.3,0.1

Type RM Length L Ch R = 1 ,9257.5  ,314.8,324.4,333.9
XS GIS Cut Line= 2
     1959433.859      405803.698     1959306.255      405975.573
#Sta/Elev= 25
       0 2195.55     9.7 2194.77    19.5 2193.51    29.2 2191.54    38.9 2188.95
    48.6 2186.12    58.4 2182.94    67.3 2180.13    68.1 2179.88    77.8 2178.27
    82.3 2178.48    87.6 2178.73    97.3 2183.37     107 2189.84   116.8 2196.04
   126.5 2201.73   136.2 2207.12     146 2211.49   155.7 2215.32   165.4 2218.96
   175.1 2222.56   184.9 2226.07   194.6 2229.46   204.3 2232.24   214.1 2234.28
#Mann= 3 , 0 , 0
       0      .1       0    67.3    .045       0    87.6      .1       0
Bank Sta=67.3,87.6
XS Rating Curve= 0 ,0
Exp/Cntr=0.3,0.1

Type RM Length L Ch R = 1 ,8933.2  ,266.8,256.2,244.4
XS GIS Cut Line= 2
     1959397.401      405501.615     1959152.609      405639.636
#Sta/Elev= 23
       0 2228.48     9.7 2224.12    19.4 2219.96    29.1 2215.99    38.8  2212.9
    48.4 2210.71    58.1 2208.72    77.5 2204.53    96.9 2199.74   106.6 2197.11
     126 2191.59   145.4 2185.54     155 2182.45   174.4  2176.8   184.1 2173.85
   193.8 2171.44   203.5 2170.68   213.2 2172.21   213.5 2172.32   222.9 2175.85
   232.6 2178.28   242.3 2178.51     281 2178.37
#Mann= 3 , 0 , 0
       0      .1       0   193.8    .045       0   213.5      .1       0
Bank Sta=193.8,213.5
XS Rating Curve= 0 ,0
Exp/Cntr=0.3,0.1

Type RM Length L Ch R = 1 ,8676.9  ,226.5,226.6,227.2
XS GIS Cut Line= 2
     1959061.463      405506.823     1958965.109      405639.636
#Sta/Elev= 20
       0  2174.3     9.6 2173.86    19.3 2173.17      29 2172.16    38.6 2170.94
    48.3 2169.58    57.4 2168.19    57.9 2168.11    67.6    2167    72.4  2167.1
    77.2  2167.2    86.9 2170.63    96.5    2176   106.2 2181.72   115.8  2187.2
   125.5 2192.84   135.1 2197.68   144.8  2201.5   154.4 2204.19   164.1 2206.56
#Mann= 3 , 0 , 0
       0      .1       0    57.4    .045       0    77.2      .1       0
Bank Sta=57.4,77.2
XS Rating Curve= 0 ,0
Exp/Cntr=0.3,0.1

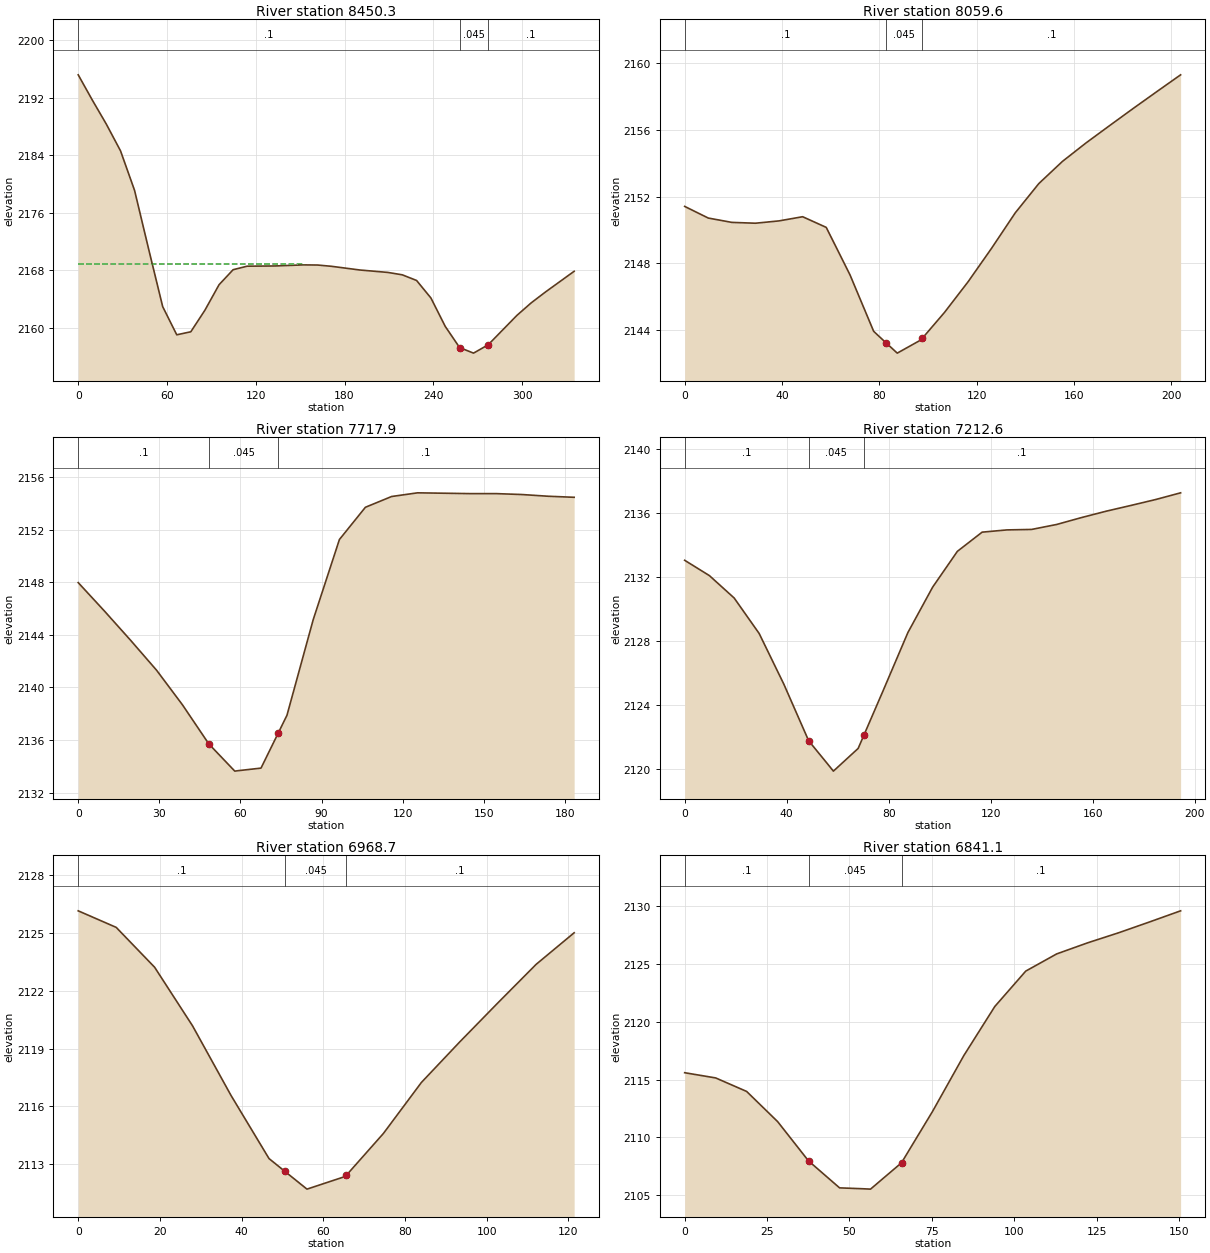
Type RM Length L Ch R = 1 ,8450.3  ,400.1,390.7,380.9
XS GIS Cut Line= 3
     1958976.828      405137.466     1958913.894      405337.118
     1958840.109      405439.115
#Sta/Elev= 30
       0 2195.19     9.5 2191.69      19 2188.33    28.6 2184.61    38.1  2179.1
    47.6 2170.94    57.1 2162.93    66.6 2159.01    76.1 2159.43    85.6 2162.42
    95.2 2165.98   104.7 2168.07   114.2 2168.56   133.2 2168.59   152.2 2168.74
   161.8 2168.72   171.3 2168.54   190.3 2168.03   209.3 2167.69     219 2167.36
   228.7 2166.57   238.4 2164.13   248.1 2160.17   257.8 2157.23   267.2 2156.46
   277.1 2157.62   296.5 2161.71   306.2 2163.46   315.9 2164.98   335.2 2167.85
#Mann= 3 , 0 , 0
       0      .1       0   257.8    .045       0   277.1      .1       0
#XS Ineff= 2 , 0
          152.32  2168.9
Permanent Ineff=
       F       F
Bank Sta=257.8,277.1
XS Rating Curve= 0 ,0
Exp/Cntr=0.3,0.1

Type RM Length L Ch R = 1 ,8059.6  ,342,341.7,341.8
XS GIS Cut Line= 2
     1958562.331      405135.296     1958521.099      405334.948
#Sta/Elev= 24
       0 2151.41     9.7 2150.71    19.4 2150.45    29.1  2150.4    38.8 2150.54
    48.5 2150.79    58.2 2150.15      68 2147.29    77.7 2143.91    82.7 2143.23
    87.4  2142.6    97.1 2143.39    97.7 2143.49   106.8 2145.04   116.5 2146.88
   126.2  2148.9   135.9 2151.02   145.6 2152.78   155.3 2154.11     165 2155.22
   174.7 2156.26   184.4 2157.29   194.2 2158.31   203.9 2159.31
#Mann= 3 , 0 , 0
       0      .1       0    82.7    .045       0    97.7      .1       0
Bank Sta=82.7,97.7
XS Rating Curve= 0 ,0
Exp/Cntr=0.3,0.1

Type RM Length L Ch R = 1 ,7717.9  ,503,505.3,507.2
XS GIS Cut Line= 2
     1958238.981         405055.     1958204.258      405235.122
#Sta/Elev= 22
       0 2147.97     9.6 2145.83    19.3  2143.6      29  2141.3    38.6 2138.66
    48.3  2135.7    57.9 2133.63      59 2133.66    67.6 2133.86      74 2136.54
    77.2 2137.88    86.9 2145.15    96.6 2151.25   106.2  2153.7   115.9 2154.52
   125.5  2154.8   135.2 2154.77   144.8 2154.74   154.5 2154.74   164.1 2154.67
   173.8 2154.54   183.4 2154.46
#Mann= 3 , 0 , 0
       0      .1       0    48.3    .045       0      74      .1       0
Bank Sta=48.3,74
XS Rating Curve= 0 ,0
Exp/Cntr=0.3,0.1

Type RM Length L Ch R = 1 ,7212.6  ,238.9,243.9,248.4
XS GIS Cut Line= 2
     1957750.699      404961.684     1957696.446      405148.316
#Sta/Elev= 23
       0 2133.06     9.7  2132.1    19.4  2130.7    29.2 2128.48    38.9  2125.3
    48.6 2121.77    55.2 2120.48    58.3 2119.87      68 2121.29    70.2  2122.1
    77.7 2124.87    87.5 2128.54    97.2 2131.38   106.9 2133.62   116.6 2134.82
   126.3 2134.96     136 2134.99   145.8  2135.3   155.5 2135.73   165.2 2136.13
   174.9 2136.49   184.6 2136.86   194.4 2137.28
#Mann= 3 , 0 , 0
       0      .1       0    48.6    .045       0    70.2      .1       0
Bank Sta=48.6,70.2
XS Rating Curve= 0 ,0
Exp/Cntr=0.3,0.1

Type RM Length L Ch R = 1 ,6968.7  ,135.2,127.6,120
XS GIS Cut Line= 2
      1957598.79      404811.945     1957548.876      404922.622
#Sta/Elev= 16
       0 2126.16     9.3  2125.3    18.7 2123.23      28 2120.18    37.4 2116.57
    46.7 2113.29    50.6 2112.62      56  2111.7    65.4 2112.36    65.6 2112.41
    74.7 2114.59      84 2117.24    93.4 2119.35   102.7 2121.37   112.1 2123.38
   121.4 2125.02
#Mann= 3 , 0 , 0
       0      .1       0    50.6    .045       0    65.6      .1       0
Bank Sta=50.6,65.6
XS Rating Curve= 0 ,0
Exp/Cntr=0.3,0.1

Type RM Length L Ch R = 1 ,6841.1  ,118,139.5,160.9
XS GIS Cut Line= 2
     1957457.731      404807.605      1957442.54      404957.344
#Sta/Elev= 19
       0  2115.6     9.4 2115.15    18.8 2113.98    28.2 2111.37    37.6 2107.96
      47 2105.63    54.2 2105.55    56.4 2105.52    65.8  2107.8    69.2 2109.41
    75.2 2112.24    84.7 2117.08    94.1 2121.33   103.5  2124.4   112.9 2125.89
   122.3 2126.85   131.7 2127.72   141.1 2128.66   150.5 2129.62
#Mann= 3 , 0 , 0
       0      .1       0    37.6    .045       0    65.8      .1       0
Bank Sta=37.6,65.8
XS Rating Curve= 0 ,0
Exp/Cntr=0.3,0.1

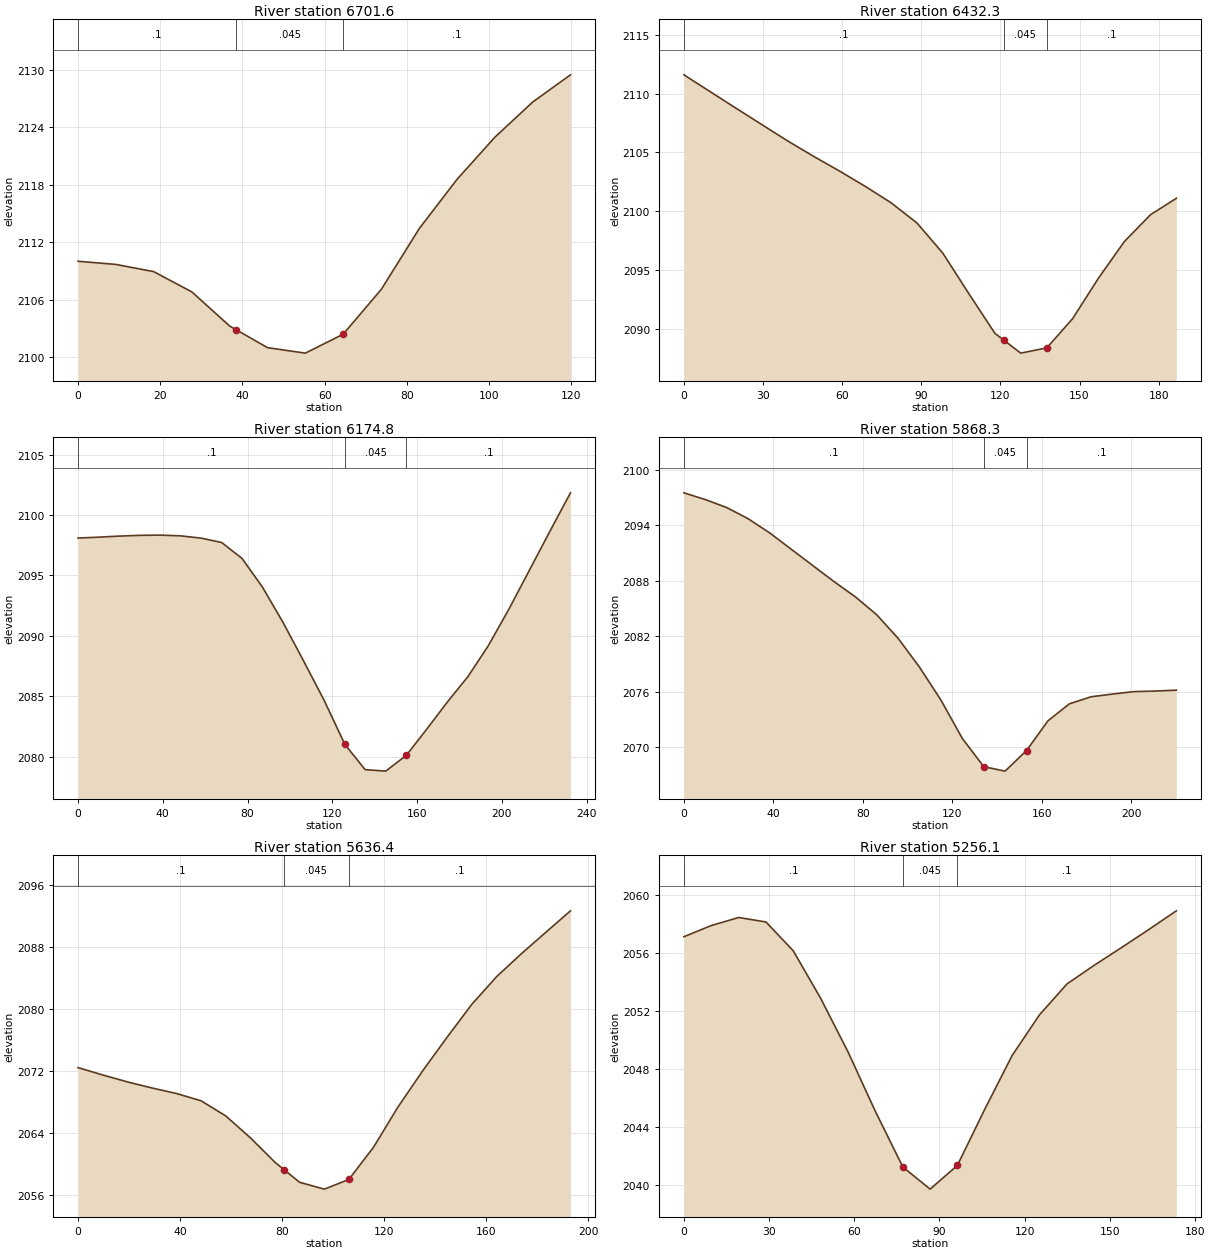
Type RM Length L Ch R = 1 ,6701.6  ,257.2,269.3,281.5
XS GIS Cut Line= 2
     1957386.116      404762.032     1957284.119      404824.966
#Sta/Elev= 16
       0 2110.02     9.2 2109.69    18.4 2108.94    27.7 2106.82    36.9 2103.26
    38.5 2102.87    46.1 2101.01    53.5 2100.55    55.3 2100.44    64.5 2102.41
    73.8  2107.1      83 2113.42    92.2 2118.56   101.4 2122.95   110.6 2126.62
   119.8 2129.46
#Mann= 3 , 0 , 0
       0      .1       0    38.5    .045       0    64.5      .1       0
Bank Sta=38.5,64.5
XS Rating Curve= 0 ,0
Exp/Cntr=0.3,0.1

Type RM Length L Ch R = 1 ,6432.3  ,279.8,257.4,235.1
XS GIS Cut Line= 2
     1957425.178      404525.487     1957238.547      404529.827
#Sta/Elev= 22
       0 2111.61     9.8  2110.2    19.6 2108.79    29.5 2107.38    39.3 2105.99
    49.1 2104.68      59 2103.42    68.8 2102.11    78.6 2100.71    88.4 2098.99
    98.2 2096.42   108.1 2092.96   117.9 2089.61   121.3 2089.02   127.7 2087.92
   136.3 2088.31   137.6 2088.37   147.4 2090.86   157.2 2094.31     167 2097.42
   176.9  2099.7   186.7  2101.1
#Mann= 3 , 0 , 0
       0      .1       0   121.3    .045       0   137.6      .1       0
Bank Sta=121.3,137.6
XS Rating Curve= 0 ,0
Exp/Cntr=0.3,0.1

Type RM Length L Ch R = 1 ,6174.8  ,306.5,306.5,306.4
XS GIS Cut Line= 2
     1957249.397      404252.049     1957123.529      404447.362
#Sta/Elev= 27
       0 2098.09     9.7 2098.16    19.4 2098.25      29 2098.31    38.7 2098.33
    48.4 2098.27    58.1 2098.08    67.8 2097.72    77.4  2096.4    87.1 2094.01
    96.8 2091.09   106.5  2087.9   116.2 2084.64   120.6    2083   125.9 2081.02
   135.5 2078.92   135.6 2078.92   145.2  2078.8   154.9  2080.1   164.6 2082.28
   174.3 2084.52     184 2086.62   193.6 2089.17   203.3 2092.19     213 2095.42
   222.7 2098.65   232.4 2101.83
#Mann= 3 , 0 , 0
       0      .1       0   125.9    .045       0   154.9      .1       0
Bank Sta=125.9,154.9
XS Rating Curve= 0 ,0
Exp/Cntr=0.3,0.1

Type RM Length L Ch R = 1 ,5868.3  ,245.3,231.9,218.7
XS GIS Cut Line= 2
     1957039.904       404024.13      1956920.89      404209.458
#Sta/Elev= 26
       0 2097.53     9.6  2096.8    19.2 2095.93    28.7 2094.73    38.3  2093.2
    47.9 2091.44    57.5 2089.68      67 2087.94    76.6 2086.28    86.2 2084.33
    95.8 2081.77   105.3 2078.67   114.9  2075.1   124.5 2070.93   134.1 2067.87
   143.6 2067.39   145.6 2067.85   153.2 2069.62   160.6  2072.1   162.8 2072.84
   172.4 2074.68     182 2075.44   191.5 2075.73   201.1    2076   210.7 2076.06
   220.2 2076.16
#Mann= 3 , 0 , 0
       0      .1       0   134.1    .045       0   153.2      .1       0
Bank Sta=134.1,153.2
XS Rating Curve= 0 ,0
Exp/Cntr=0.3,0.1

Type RM Length L Ch R = 1 ,5636.4  ,377.4,380.3,383.2
XS GIS Cut Line= 2
     1956756.776       404104.48     1956756.776      404297.622
#Sta/Elev= 23
       0 2072.45     9.7  2071.5    19.3 2070.61      29 2069.82    38.6 2069.11
    48.3 2068.16    57.9 2066.22    67.6 2063.39    77.3 2060.21    80.7  2059.3
    86.9 2057.65    95.7 2056.85    96.6 2056.77   106.2 2058.02   115.9 2062.19
   125.5 2067.39   135.2 2072.06   144.9 2076.45   154.5 2080.65   164.2 2084.21
   173.8 2087.13   183.5 2089.93   193.1 2092.68
#Mann= 3 , 0 , 0
       0      .1       0    80.7    .045       0   106.2      .1       0
Bank Sta=80.7,106.2
XS Rating Curve= 0 ,0
Exp/Cntr=0.3,0.1

Type RM Length L Ch R = 1 ,5256.1  ,292.1,284.8,277.5
XS GIS Cut Line= 2
     1956429.085      403998.143     1956403.043      404169.584
#Sta/Elev= 21
       0 2057.15     9.6 2057.92    19.3 2058.48    28.9 2058.17    38.5 2056.18
    48.2 2052.88    57.8 2049.19    67.4 2045.09    77.1 2041.24    85.5  2039.9
    86.7 2039.71    96.3 2041.35   100.5 2043.04     106 2045.25   115.6 2048.95
   125.2 2051.75   134.9 2053.89   144.5 2055.18   154.1  2056.4   163.8 2057.66
   173.4 2058.94
#Mann= 3 , 0 , 0
       0      .1       0    77.1    .045       0    96.3      .1       0
Bank Sta=77.1,96.3
XS Rating Curve= 0 ,0
Exp/Cntr=0.3,0.1