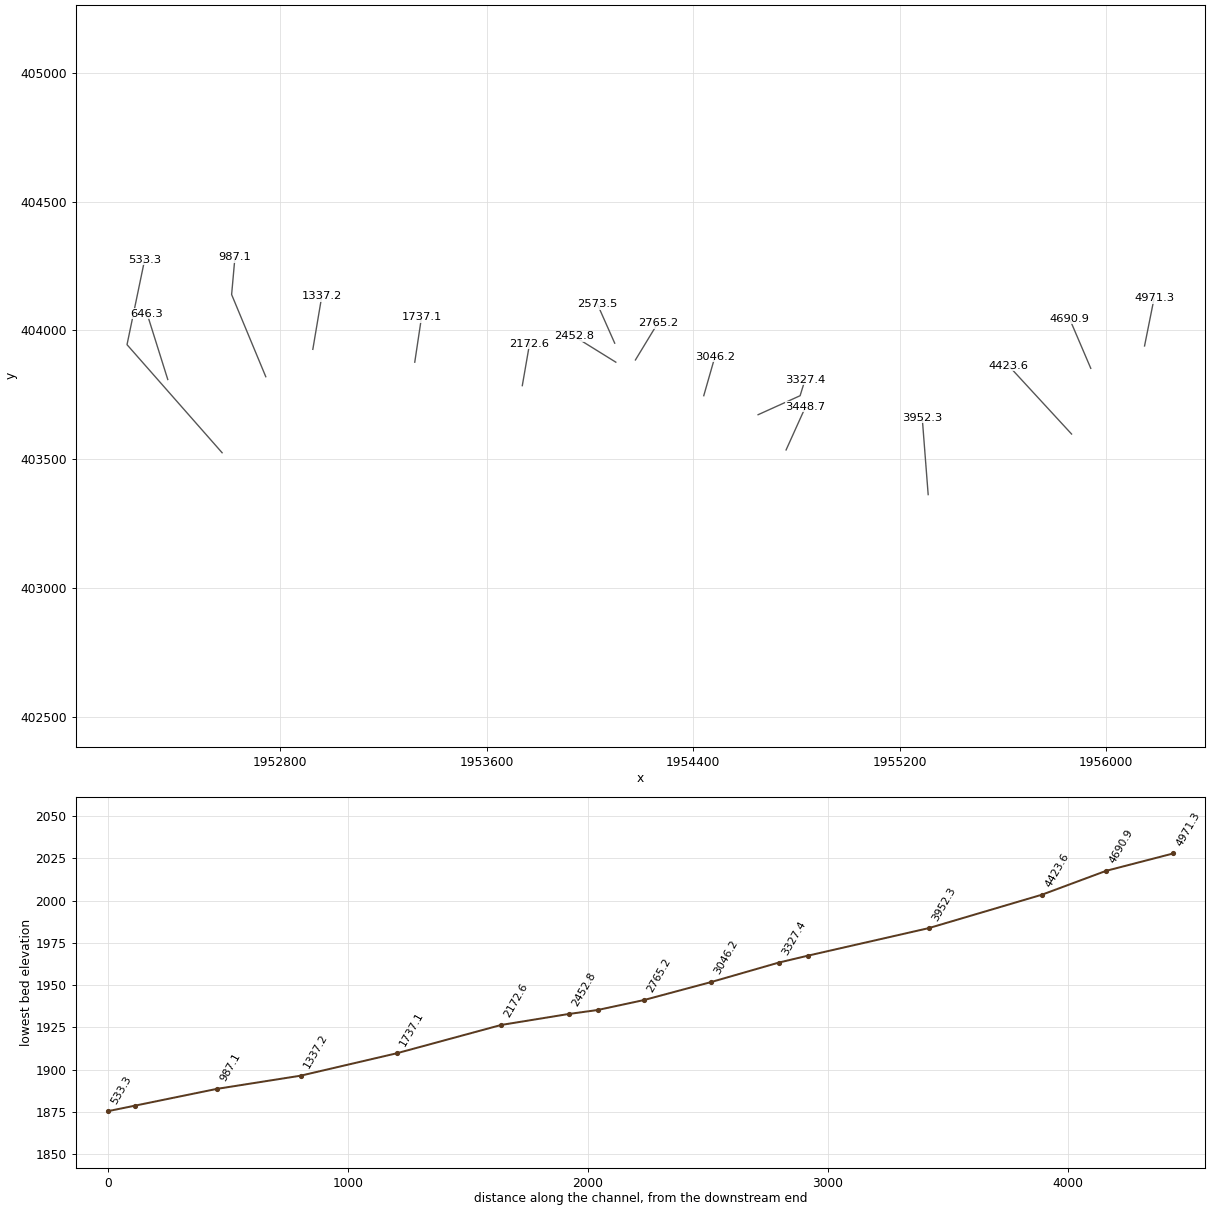
HEC-RAS study BEAVERCRK.prj: BEAVERCRK

--- BEAVERCRK.g01 (geometry) --- (continued)

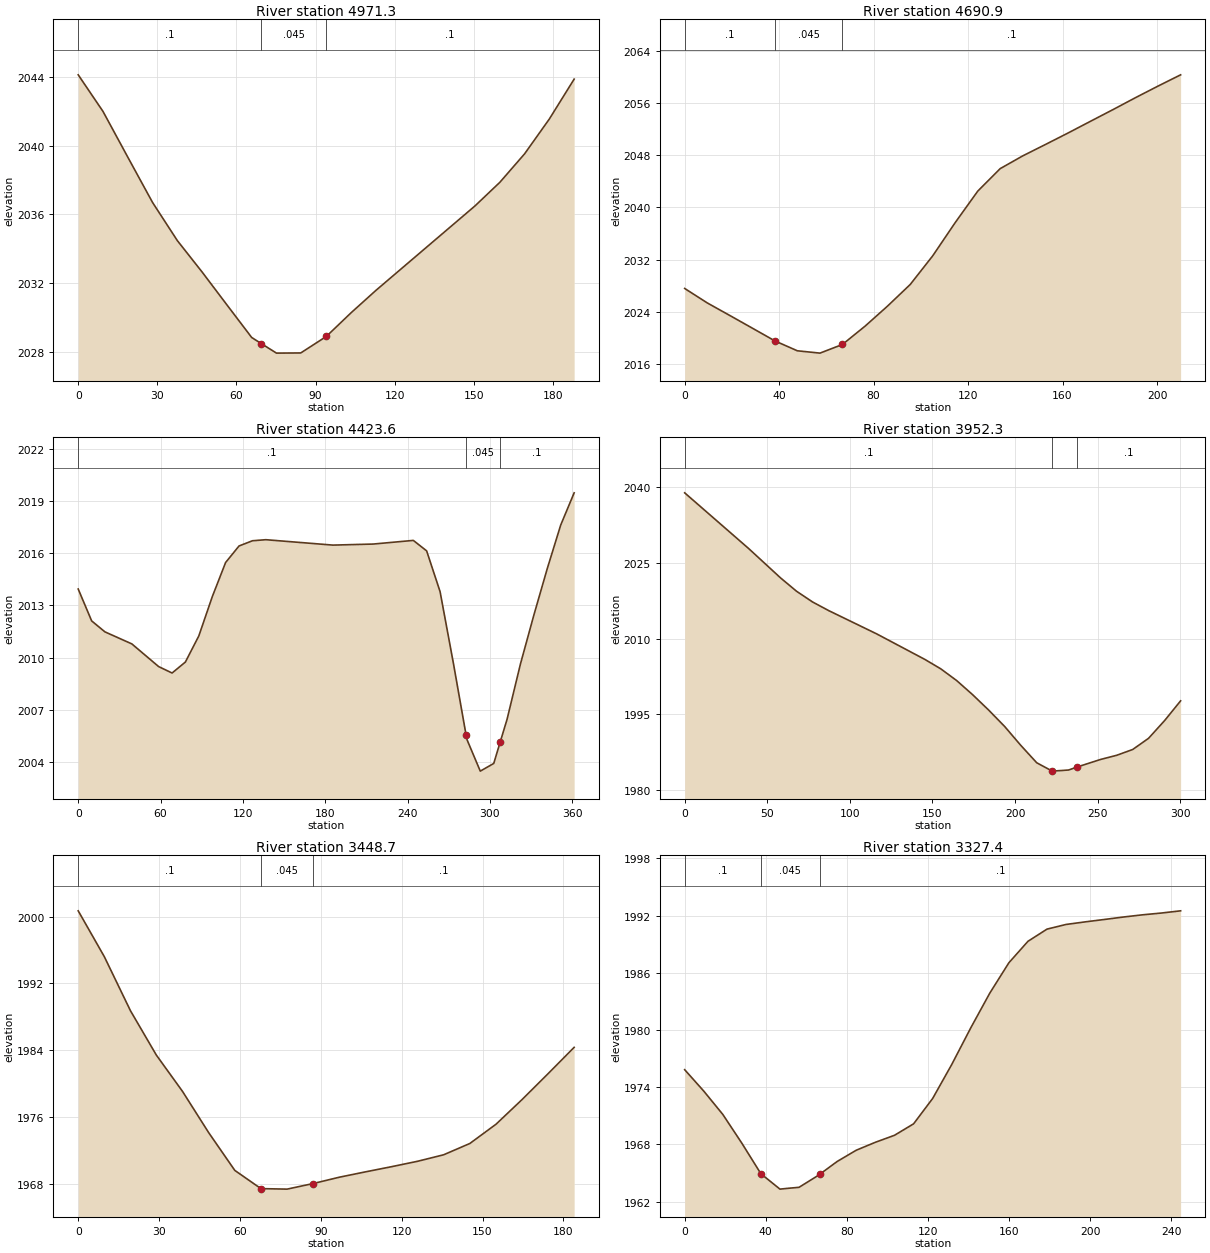
Type RM Length L Ch R = 1 ,4971.3  ,266.7,280.4,294.1
XS GIS Cut Line= 2
     1956149.137      403939.549     1956186.029      404124.011
#Sta/Elev= 22
       0 2044.13     9.4    2042    18.8 2039.34    28.2  2036.7    37.6 2034.48
      47 2032.65    56.4 2030.74    65.8 2028.84    69.4 2028.49    75.2 2027.93
    84.4 2027.94    94.1  2028.9   103.5 2030.28   112.9 2031.58   122.3 2032.81
   131.7 2034.04   141.1 2035.27   150.5  2036.5   159.9 2037.87   169.3 2039.53
   178.7 2041.56   188.1 2043.88
#Mann= 3 , 0 , 0
       0      .1       0    69.4    .045       0    94.1      .1       0
Bank Sta=69.4,94.1
XS Rating Curve= 0 ,0
Exp/Cntr=0.3,0.1

Type RM Length L Ch R = 1 ,4690.9  ,259.6,267.3,275
XS GIS Cut Line= 2
     1955940.803      403852.743     1955858.338      404045.886
#Sta/Elev= 25
       0 2027.55     9.6 2025.32    19.1  2023.4    28.6 2021.46    38.2 2019.49
    47.7 2017.97    57.3 2017.61      60 2017.99    66.8 2018.94      75 2021.35
    76.4 2021.76    85.9 2024.84    95.5 2028.16     105 2032.55   114.6  2037.7
   124.1 2042.51   133.6 2045.97   143.2 2047.94   152.7 2049.67   162.3 2051.44
   171.8 2053.24   181.4 2055.05   190.9 2056.88   200.5 2058.67     210 2060.39
#Mann= 3 , 0 , 0
       0      .1       0    38.2    .045       0    66.8      .1       0
Bank Sta=38.2,66.8
XS Rating Curve= 0 ,0
Exp/Cntr=0.3,0.1

Type RM Length L Ch R = 1 ,4423.6  ,486.8,471.4,455.9
XS GIS Cut Line= 2
     1955866.402      403597.611     1955621.793      403863.594
#Sta/Elev= 30
       0 2013.94     9.8 2012.11    19.5 2011.48    39.1 2010.79    58.6 2009.49
    68.4 2009.12    78.1 2009.75    87.9 2011.25    97.7  2013.5   107.4 2015.46
   117.2 2016.41     127 2016.71   136.7 2016.77   185.6 2016.46   214.9 2016.52
   244.2 2016.73   253.9 2016.13   263.7 2013.79   273.5 2009.64   282.7 2005.54
   283.2 2005.32     293 2003.49   302.8 2003.93  307.612005.185   312.5 2006.46
   322.3 2009.65   332.1 2012.46   341.8 2015.11   351.6 2017.61   361.4 2019.46
#Mann= 3 , 0 , 0
       0      .1       0   282.7    .045       0  307.61      .1       0
Bank Sta=282.7,307.61
XS Rating Curve= 0 ,0
Exp/Cntr=0.3,0.1

Type RM Length L Ch R = 1 ,3952.3  ,515,503.6,492.2
XS GIS Cut Line= 2
     1955310.775       403362.45     1955287.592      403661.771
#Sta/Elev= 24
       0  2038.9    38.7 2027.86    58.1 2022.01    67.8 2019.36    77.5 2017.24
    87.2 2015.54   116.2 2010.93   145.3 2005.88     155    2004   164.6 2001.68
   174.3 1998.87     184 1995.82   193.7 1992.56   203.4 1988.84   213.1 1985.37
   222.5 1983.71   232.4 1983.93   237.5 1984.52   251.8 1986.03   261.5 1986.85
   271.2    1988   280.8 1990.22   290.5 1993.73   300.2 1997.65
#Mann= 3 , 0 , 0
       0      .1       0   222.5    .045       0   237.5      .1       0
Bank Sta=222.5,237.5
XS Rating Curve= 0 ,0
Exp/Cntr=0.3,0.1

Type RM Length L Ch R = 1 ,3448.7  ,138,121.3,104.6
XS GIS Cut Line= 2
     1954760.248      403535.903     1954835.841      403703.665
#Sta/Elev= 22
       0 2000.69     9.7  1995.2    19.4 1988.73      29 1983.43    38.7 1979.09
    48.4 1974.16    58.1 1969.64    67.8 1967.46    77.5  1967.4    82.7 1967.76
    87.2 1968.07    96.8 1968.82    97.7 1968.88   106.5 1969.46   116.2 1970.08
   125.9 1970.73   135.6 1971.51   145.3 1972.86     155 1975.16   164.6 1978.09
   174.3  1981.2     184 1984.36
#Mann= 3 , 0 , 0
       0      .1       0    67.8    .045       0    87.2      .1       0
Bank Sta=67.8,87.2
XS Rating Curve= 0 ,0
Exp/Cntr=0.3,0.1

Type RM Length L Ch R = 1 ,3327.4  ,261.3,281.3,301.2
XS GIS Cut Line= 3
     1954651.741      403672.622     1954814.501      403746.407
     1954834.033      403809.341
#Sta/Elev= 29
       0 1975.83     9.4 1973.59    18.8 1971.14    28.2 1968.12    37.6 1964.91
      47  1963.3    51.7  1963.4    56.4 1963.49    65.8 1964.73    66.7 1964.87
    75.2  1966.2    84.6 1967.38      94 1968.21   103.5 1968.95   112.9 1970.15
   122.3 1972.81   131.7 1976.37   141.1 1980.22   150.5 1983.87   159.9 1987.05
   169.3  1989.3   178.7 1990.58   188.1 1991.07   197.5 1991.34   206.9 1991.59
   216.4 1991.85   225.8 1992.08   235.2 1992.27   244.6  1992.5
#Mann= 3 , 0 , 0
       0      .1       0    37.6    .045       0    66.7      .1       0
Bank Sta=37.6,66.7
XS Rating Curve= 0 ,0
Exp/Cntr=0.3,0.1

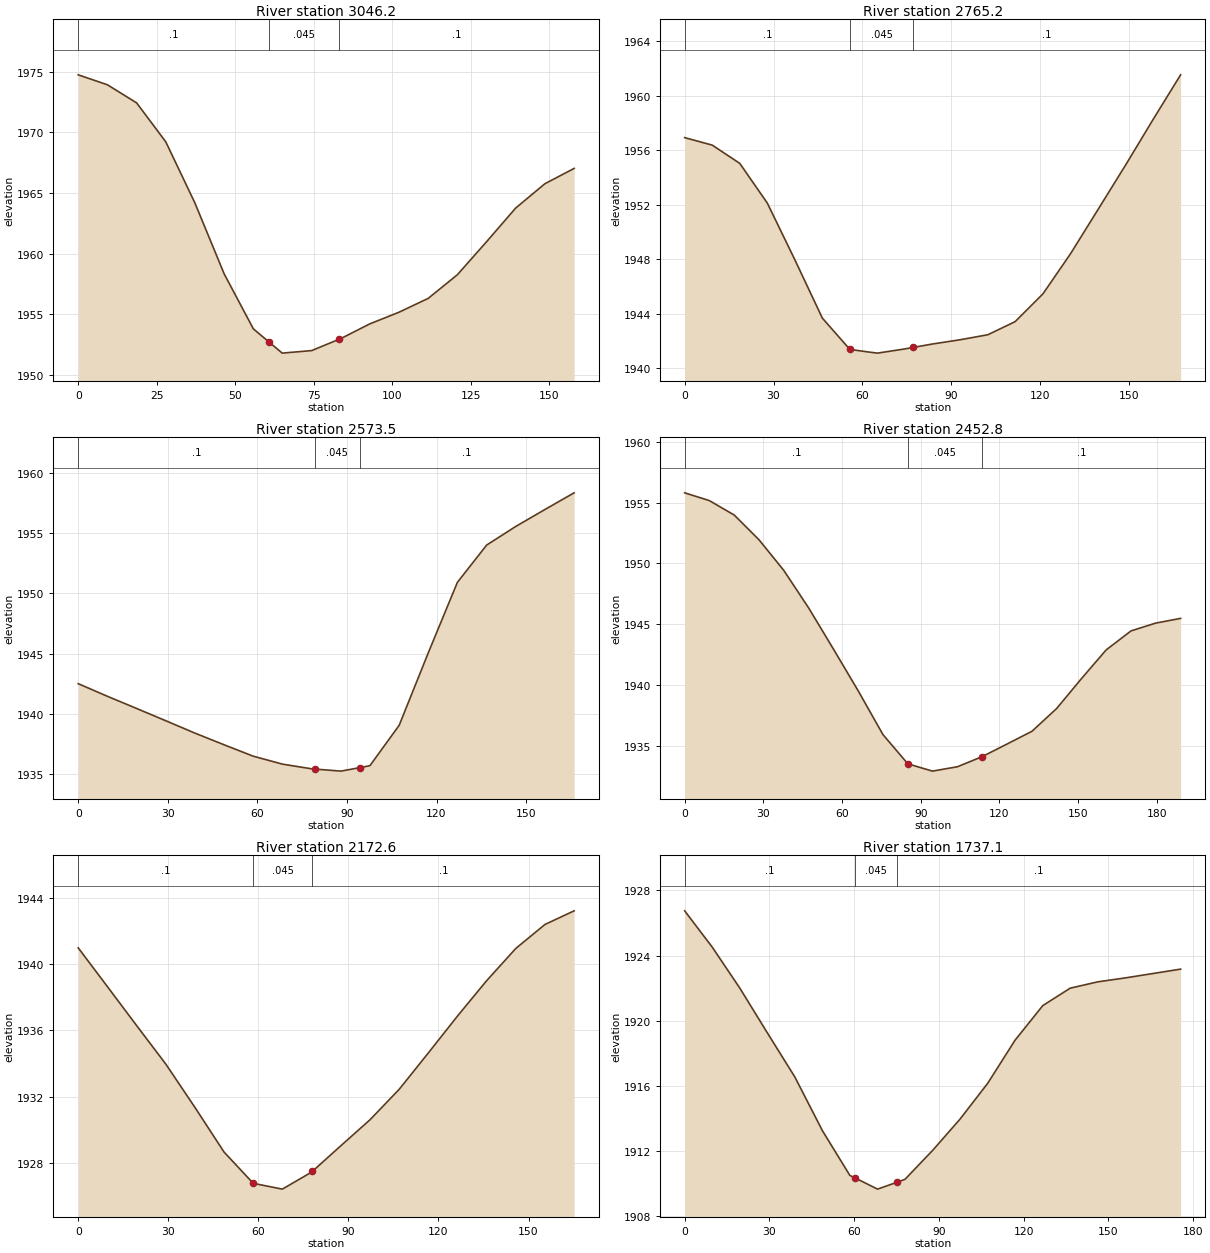
Type RM Length L Ch R = 1 ,3046.2  ,287.1,281,274.9
XS GIS Cut Line= 2
     1954441.238      403746.407      1954484.64      403898.316
#Sta/Elev= 21
       0 1974.73     9.3 1973.91    18.6 1972.42    27.9 1969.21    37.2 1964.16
    46.5 1958.33    55.8  1953.8   60.851952.702      65  1951.8    68.1 1951.87
    74.4 1952.01    83.1 1952.94    83.6 1952.99    92.9 1954.21   102.2 1955.17
   111.5 1956.31   120.8 1958.26   130.1 1960.98   139.4 1963.76   148.7 1965.76
     158 1967.02
#Mann= 3 , 0 , 0
       0      .1       0   60.85    .045       0    83.1      .1       0
Bank Sta=60.85,83.1
XS Rating Curve= 0 ,0
Exp/Cntr=0.3,0.1

Type RM Length L Ch R = 1 ,2765.2  ,169.9,191.7,214.2
XS GIS Cut Line= 2
     1954176.481      403885.296     1954263.286      404028.525
#Sta/Elev= 21
       0 1956.93     9.3 1956.38    18.6 1955.04    27.9 1952.13    37.2 1947.97
    46.5 1943.68    55.8 1941.38    62.2 1941.19    65.1 1941.11    74.4 1941.42
    77.2 1941.53    83.7 1941.78      93 1942.09   102.4 1942.46   111.6 1943.42
     121 1945.46   130.3  1948.4   139.6 1951.65   148.9 1954.91   158.2 1958.26
   167.5 1961.54
#Mann= 3 , 0 , 0
       0      .1       0    55.8    .045       0    77.2      .1       0
Bank Sta=55.8,77.2
XS Rating Curve= 0 ,0
Exp/Cntr=0.3,0.1

Type RM Length L Ch R = 1 ,2573.5  ,107.4,120.7,132.5
XS GIS Cut Line= 2
     1954096.185        403950.4     1954028.911      404102.309
#Sta/Elev= 20
       0 1942.51     9.8 1941.46    19.6 1940.45    29.3 1939.44    39.1 1938.41
    48.9 1937.44    58.6  1936.5    68.4 1935.84    78.2 1935.45    79.3 1935.43
      88 1935.26    94.3 1935.55    97.7 1935.71   107.5 1939.06   117.3  1945.1
     127 1950.91   136.8    1954   146.6 1955.55   156.4 1956.96   166.1 1958.33
#Mann= 3 , 0 , 0
       0      .1       0    79.3    .045       0    94.3      .1       0
Bank Sta=79.3,94.3
XS Rating Curve= 0 ,0
Exp/Cntr=0.3,0.1

Type RM Length L Ch R = 1 ,2452.8  ,307.5,280.2,252.9
XS GIS Cut Line= 2
     1954100.526      403876.615     1953939.935      403976.441
#Sta/Elev= 22
       0 1955.82     9.4 1955.18    18.9 1953.99    28.4 1951.94    37.8 1949.43
    47.3 1946.33    56.7 1942.96    66.2  1939.5    75.6 1935.91    85.1  1933.5
    94.5  1932.9    98.4 1933.05     104 1933.26   113.4 1934.09   122.9 1935.13
   132.4 1936.18   141.8 1938.05   151.3 1940.52   160.7 1942.88   170.2 1944.45
   179.6 1945.09   189.1 1945.48
#Mann= 3 , 0 , 0
       0      .1       0    85.1    .045       0   113.4      .1       0
Bank Sta=85.1,113.4
XS Rating Curve= 0 ,0
Exp/Cntr=0.3,0.1

Type RM Length L Ch R = 1 ,2172.6  ,435.1,435.5,435.8
XS GIS Cut Line= 2
     1953738.113      403785.469     1953766.324       403948.23
#Sta/Elev= 20
       0 1940.97     9.7 1938.64    19.4  1936.3    29.2 1933.96    38.9 1931.35
    48.6 1928.66    58.3 1926.78      63 1926.61      68 1926.43    77.7 1927.45
      78  1927.5    87.4 1929.03    97.2 1930.61   106.9 1932.44   116.6 1934.63
   126.3 1936.85     136 1938.98   145.8 1940.94   155.5 1942.38   165.2  1943.2
#Mann= 3 , 0 , 0
       0      .1       0    58.3    .045       0      78      .1       0
Bank Sta=58.3,78
XS Rating Curve= 0 ,0
Exp/Cntr=0.3,0.1

Type RM Length L Ch R = 1 ,1737.1  ,400.2,399.8,399.5
XS GIS Cut Line= 2
     1953321.446      403876.615     1953347.488      404050.226
#Sta/Elev= 21
       0 1926.75     9.8 1924.51    19.5 1922.01    29.3 1919.25      39 1916.55
    48.8 1913.24    58.5  1910.5    60.3 1910.35    68.3 1909.66    75.3 1910.09
      78 1910.26    87.8 1912.04    97.5 1913.96   107.3 1916.16     117 1918.81
   126.8 1920.93   136.5    1922   146.3 1922.39     156 1922.63   165.8  1922.9
   175.6 1923.17
#Mann= 3 , 0 , 0
       0      .1       0    60.3    .045       0    75.3      .1       0
Bank Sta=60.3,75.3
XS Rating Curve= 0 ,0
Exp/Cntr=0.3,0.1

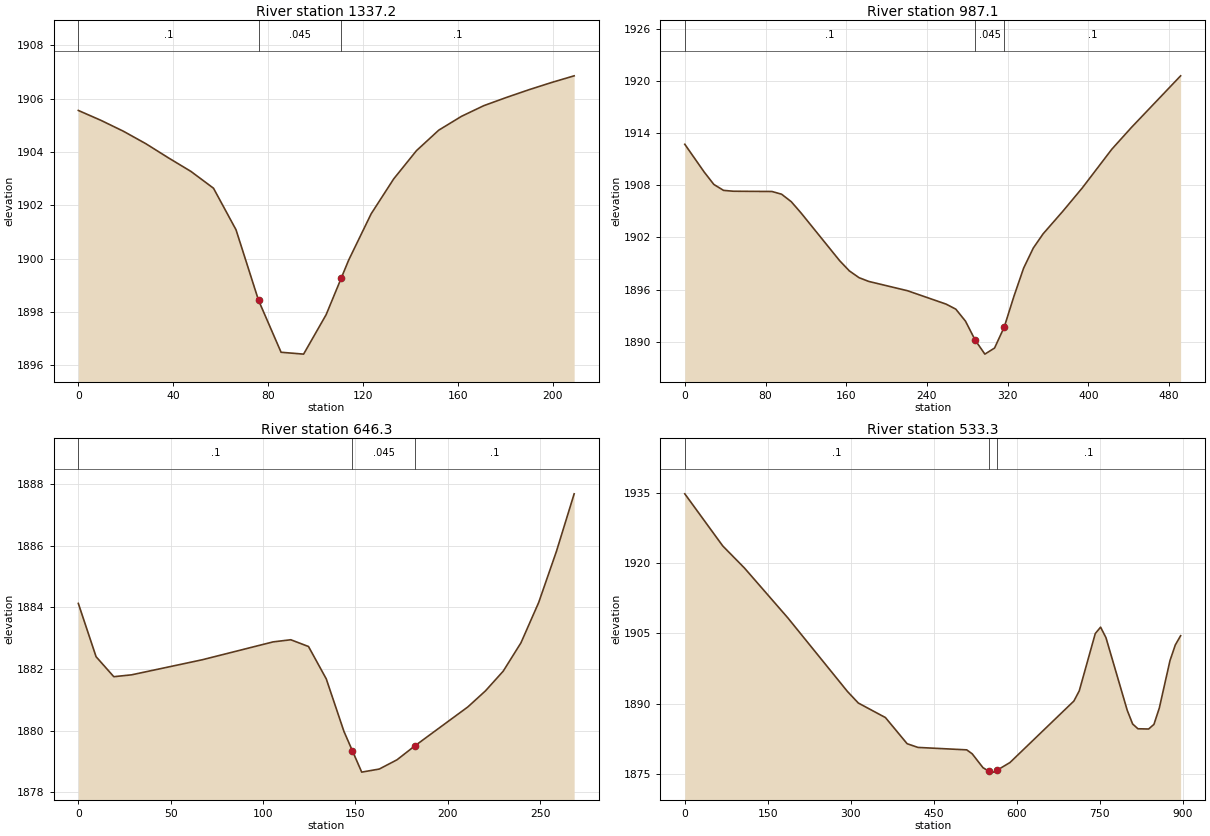
Type RM Length L Ch R = 1 ,1337.2  ,336.7,350.1,363.4
XS GIS Cut Line= 2
     1952926.481      403926.528     1952961.203      404132.691
#Sta/Elev= 25
       0 1905.56     9.5 1905.19      19 1904.78    28.5 1904.31      38 1903.78
    47.5 1903.27      57 1902.64    66.5 1901.08      76 1898.43    85.5 1896.48
      95 1896.41    95.9 1896.55   104.5 1897.89   110.9 1899.27     114 1899.94
   123.5 1901.68     133 1902.99   142.6 1904.05     152 1904.82   161.6 1905.34
     171 1905.74   180.6 1906.05   190.1 1906.34   199.6 1906.61   209.1 1906.86
#Mann= 3 , 0 , 0
       0      .1       0      76    .045       0   110.9      .1       0
Bank Sta=76,110.9
XS Rating Curve= 0 ,0
Exp/Cntr=0.3,0.1

Type RM Length L Ch R = 1 ,987.1   ,343,340.8,338.7
XS GIS Cut Line= 3
     1952744.189      403820.191      1952611.81      404139.202
     1952624.831      404284.601
#Sta/Elev= 30
       0  1912.7    19.2 1909.51    28.8 1908.08    38.4  1907.4      48  1907.3
    86.4 1907.27    95.9 1906.96   105.5  1906.1   115.1 1904.82   153.5 1899.31
   163.1 1898.14   172.7 1897.36   182.3 1896.93   220.7 1895.86     259 1894.32
   268.6 1893.74   278.2 1892.36   287.8 1890.18   297.4 1888.57     307 1889.27
   316.6 1891.69   326.2 1895.22   335.8 1898.46   345.4 1900.77   355.1  1902.4
   374.6 1904.99     394 1907.69   423.2 1912.13   442.7 1914.64   491.4 1920.57
#Mann= 3 , 0 , 0
       0      .1       0   287.8    .045       0   316.6      .1       0
Bank Sta=287.8,316.6
XS Rating Curve= 0 ,0
Exp/Cntr=0.3,0.1

Type RM Length L Ch R = 1 ,646.3   ,103.3,113,94.1
XS GIS Cut Line= 2
     1952364.415      403809.341     1952284.119      404065.417
#Sta/Elev= 22
       0 1884.13     9.6  1882.4    19.2 1881.75    28.8 1881.81    67.1  1882.3
   105.4 1882.88     115 1882.95   124.6 1882.73   134.2 1881.68   143.8 1879.97
  148.31 1879.35   153.4 1878.65   162.9 1878.75   172.5 1879.05   182.1  1879.5
   210.9 1880.77   220.4 1881.29     230 1881.93   239.6 1882.85   249.2 1884.16
   258.8 1885.82   268.4 1887.69
#Mann= 3 , 0 , 0
       0      .1       0  148.31    .045       0   182.1      .1       0
Bank Sta=148.31,182.1
XS Rating Curve= 0 ,0
Exp/Cntr=0.3,0.1

Type RM Length L Ch R = 1 ,533.3   ,564.6,533.3,529.7
XS GIS Cut Line= 3
        1952575.         403525.     1952206.534      403944.626
        1952275.         404275.
#Sta/Elev= 30
       0 1934.74    68.6 1923.62   107.8 1918.91   186.2 1908.27   293.9 1892.57
   313.5 1890.11   362.5 1887.01   401.7 1881.43   421.3 1880.64   509.4 1880.12
   519.2 1879.28   538.8 1876.31   549.9 1875.53   558.4 1875.37   564.9 1875.83
   587.4 1877.41     703 1890.54   712.7 1892.72   741.6 1904.93   751.2  1906.3
   760.9 1904.06   799.4 1888.54   809.1 1885.64   818.7 1884.62     838 1884.57
   847.6 1885.56   857.3 1889.04   876.6 1899.17   886.2  1902.5   895.8 1904.47
#Mann= 3 , 0 , 0
       0      .1       0   549.9    .045       0   564.9      .1       0
Bank Sta=549.9,564.9
XS Rating Curve= 0 ,0
Exp/Cntr=0.3,0.1

Chan Stop Cuts=-1
Use User Specified Reach Order=0
Composite Channel Slope=5